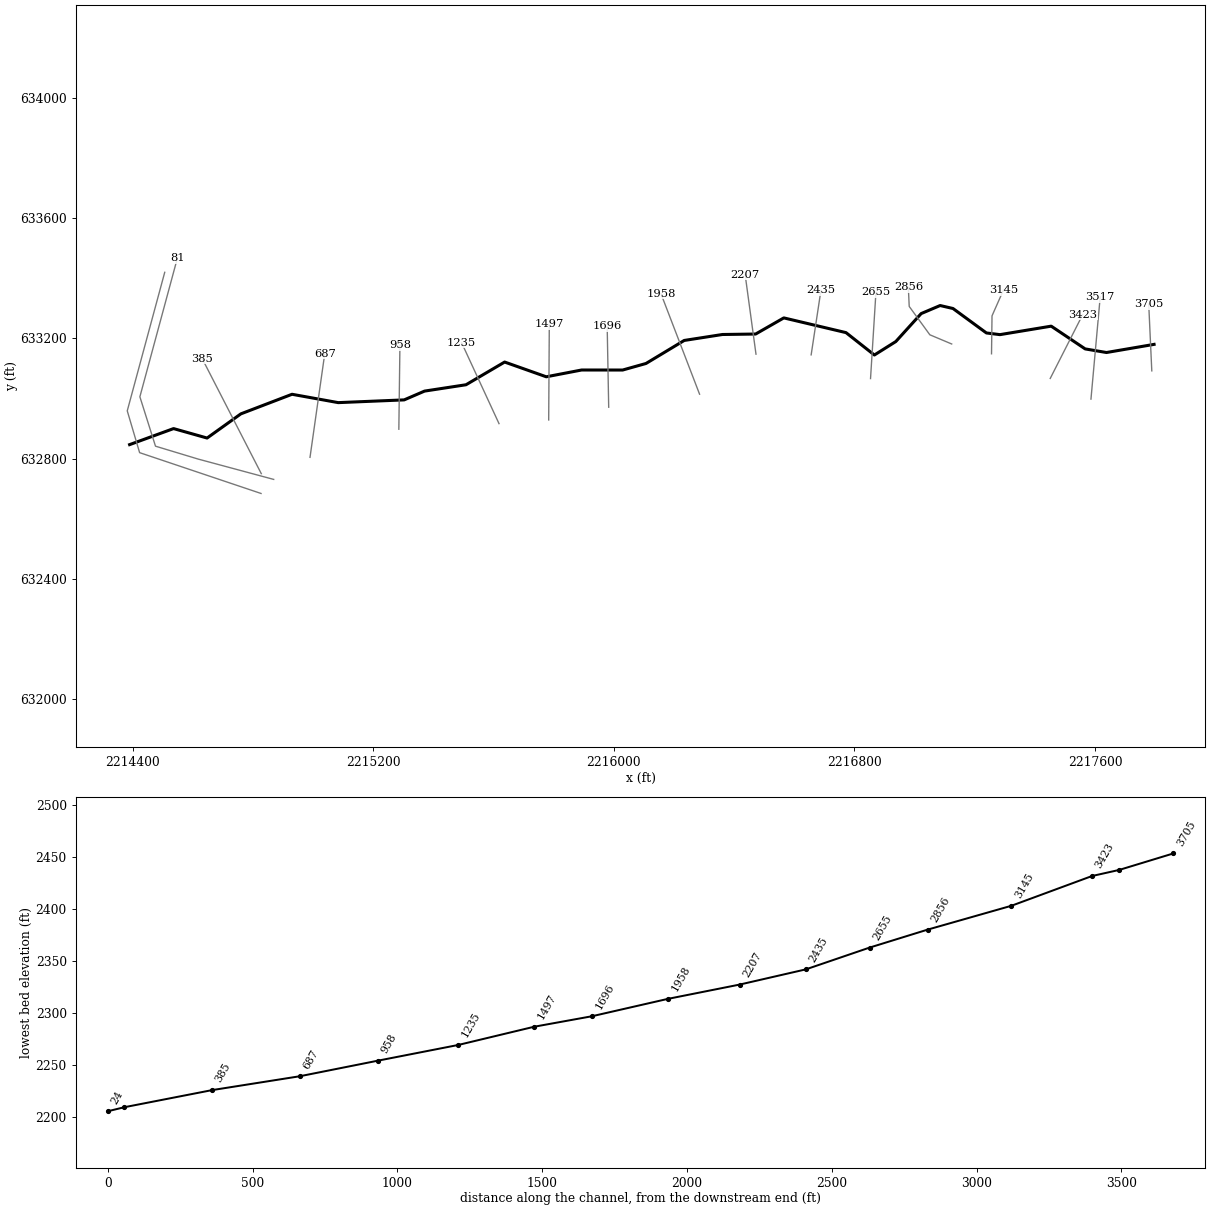
--- LDRYRN.prj (project) ---

Proj Title=LDRYRN
Current Plan=p01
Default Exp/Contr=0,0
English Units
Geom File=g01
Flow File=f01
Plan File=p01
BEGIN DESCRIPTION:
----------MODEL BY WOOD PLC 2022----------
AFH study
Randolph County, WV
HEC-RAS Version: RAS 6.2
Vertical Datum: NAVD88
Projection: NAD 1983 StatePlane West Virginia S FIPS 4702 (US Feet)
Terrain: 1-meter LIDAR (FEMA Region III 3DEP collected 2016-2018)
Land Use: 2019 NLCD
Hydrologic Method:
WV SIR2010-5033 regression equations
Additional Model Notes:
None
END DESCRIPTION:
DSS File=dss
DSS Export Rating Curves= 0
DSS Export Rating Curve Sorted= 0
DSS Export Volume Flow Curves= 0
DXF OffsetX= 0
DXF OffsetY= 0
DXF ScaleX= 0
DXF ScaleY= 0

--- LDRYRN.p01 (plan) ---

Plan Title=Floodplain
Program Version=6.20
Short Identifier=Floodplain
Geom File=g01
Flow File=f01
Subcritical Flow
K Sum by GR= 0
Std Step Tol= 0.01
Critical Tol= 0.01
Num of Std Step Trials= 20
Max Error Tol= 0.3
Flow Tol Ratio= 0.001
Split Flow NTrial= 30
Split Flow Tol= 0.02
Split Flow Ratio= 0.02
Log Output Level= 0
Friction Slope Method= 1
Unsteady Friction Slope Method= 2
Unsteady Bridges Friction Slope Method= 1
Parabolic Critical Depth
Global Vel Dist= 0 , 0 , 0
Global Log Level= 0
CheckData=False
Encroach Param=-1 ,0,0, 0
Computation Interval=0.1SEC
Output Interval=1SEC
Instantaneous Interval=Max Profile
Mapping Interval=1HOUR
Computation Time Step Use Courant=        0
Computation Time Step Use Time Series=    0
Computation Time Step Count To Double=0
Computation Time Step Max Doubling=0
Computation Time Step Max Halving=0
Computation Time Step Residence Courant=0
Run HTab= 0
Run UNet= 0
Run Sediment= 0
Run PostProcess= 0
Run WQNet= 0
Run RASMapper=-1
UNET Theta= 0
UNET Theta Warmup= 0
UNET ZTol= 0
UNET ZSATol= 0
UNET MxIter= 0
UNET Max Iter WO Improvement= 0
UNET MaxInSteps= 0
UNET DtIC= 0
UNET DtMin= 0
UNET MaxCRTS= 0
UNET WFStab= 0
UNET SFStab= 0
UNET WFX= 1
UNET SFX= 1
UNET Gravity=32.174
UNET 1D Methodology=Finite Difference
UNET DSS MLevel= 1
UNET Pardiso=0
UNET DZMax Abort= 0
UNET Use Existing IB Tables= 0
UNET Froude Reduction=False
UNET Froude Limit= 0
UNET Froude Power= 0
UNET D1 Cores= 0
UNET WindReference=Eulerian
UNET WindDragFormulation=Hsu (1988)
UNET D2 Coriolis=0
UNET D2 Cores= 0
UNET D2 Theta= 1
UNET D2 Theta Warmup= 1
UNET D2 Z Tol= 0.01
UNET D2 Volume Tol= 0.01
UNET D2 Max Iterations= 20
UNET D2 Equation= 0
UNET D2 RampUpFraction=0.1
UNET D2 TimeSlices= 1
UNET D2 Turbulence Formulation=Non-Conservative (original)
UNET D2 Eddy Viscosity=0.3
UNET D2 Transverse Eddy Viscosity=0.1
UNET D2 Smagorinsky Mixing=0
UNET D2 BCVolumeCheck=0
UNET D2 Cores=0
UNET D2 SolverType=PARDISO (Direct)
UNET D2 Minimum Iterations= 2147483647
UNET D2 Maximum Iterations= 2147483647
UNET D2 Restart Number= 10
UNET D2 Relaxation Coeff=1.3
UNET D2 SOR Precondition Iterations= 10
UNET D2 ILUT Maximum Fill= 8
UNET D2 ILUT Tolerance=1E-08
UNET D1D2 MaxIter= 0
UNET D1D2 ZTol=0.01
UNET D1D2 QTol=0.1
UNET D1D2 MinQTol=1
DSS File=dss
Write IC File= 0
Write IC File at Fixed DateTime=0
Write IC File at Sim End=0
Echo Input=False
Echo Parameters=False
Echo Output=False
Write Detailed= 0
HDF Write Warmup=0
HDF Write Time Slices=0
HDF Flush=0
HDF Compression= 1
HDF Chunk Size= 1
HDF Spatial Parts= 1
HDF Use Max Rows=0
HDF Fixed Rows= 1
Calibration Method= 0
Calibration Iterations= 20
Calibration Max Change=0.05
Calibration Tolerance=0.2
Calibration Maximum=1.5
Calibration Minimum=0.5
Calibration Optimization Method= 1
WQ AD Non Conservative
WQ ULTIMATE=-1
WQ Max Comp Step=1HOUR
WQ Output Interval=15MIN
WQ Output Selected Increments= 0
WQ Output face flow=0
WQ Output face velocity=0
WQ Output face area=0
WQ Output face dispersion=0
WQ Output cell volume=0
WQ Output cell surface area=0
WQ Output cell continuity=0
WQ Output cumulative cell continuity=0
WQ Output face conc=0
WQ Output face dconc_dx=0
WQ Output face courant=0
WQ Output face peclet=0
WQ Output face adv mass=0
WQ Output face disp mass=0
WQ Output cell mass=0
WQ Output cell source sink temp=0
WQ Output nsm pathways=0
WQ Output nsm derived pathways=0
WQ Create Restart=0
WQ Fixed Restart=0
WQ System Summary=0
WQ Write To DSS=0
Sorting and Armoring Iterations= 10
XS Update Threshold= 0.02
Bed Roughness Predictor= 0
Hydraulics Update Threshold= 0.02
Energy Slope Method= 1
Volume Change Method= 1
Sediment Retention Method= 0
Sediment TS Multiplier= 1
Warm Up Method= 0
XS Weighting Method= 0
Number of US Weighted Cross Sections= 1
Number of DS Weighted Cross Sections= 1
Upstream XS Weight=0
Main XS Weight=1
Downstream XS Weight=0
Number of DS XS's Weighted with US Boundary= 1
Upstream Boundary Weight= 1
Weight of XSs Associated with US Boundary= 0
Number of US XS's Weighted with DS Boundary= 1
Downstream Boundary Weight= 0.5
Weight of XSs Associated with DS Boundary= 0.5
Percentile Method= 0
Sediment Output Level= 3
Mass or Volume Output= 0
Output Increment Type= 1
Profile and TS Output Increment= 1
Transport Output Increment 1
XS Output Flag= 0
XS Output Increment= 10
Read HDF5 Sediment Hotstart= 0
Sediment Hotstart Type= 0
Write Gradation File= 0
Read Gradation Hotstart= 0
Write HDF5 File= 1
Write Binary Output= 1
Write DSS Sediment File= 0
DSS Sediment Output Type= 1
SV Curve= 0
Specific Gage Flag= 0
Subcell Erosion Methods= 0
Subcell Deposition Methods= 0
Advection Scheme= 1
Matrix Solver= 0
Implicit Weighting Factor= 1
Maximum Outer Loop Convergence Iterations= 5
Convergence Maximum Absolute= 0.001
Convergence RMSE= 0.0001
Grain Fractions Max Abs Error= 0.001
Max Subgrid Regions= 1
Max Subgrid Length Scale= 3.402823E+38
Initial Layer Thickness= 3.402823E+38
Min Layer Thickness= 3.402823E+38
Max Layer Thickness= 3.402823E+38
Number of Layers= 5

--- LDRYRN.f01 (steady flow) ---

Flow Title=Flow
Program Version=6.20
Number of Profiles= 1
Profile Names=P100yr
River Rch & RM=LDRYRN,Main            ,3705
     365
River Rch & RM=LDRYRN,Main            ,1497
     410
Boundary for River Rch & Prof#=LDRYRN,Main            , 1
Up Type= 0
Dn Type= 3
Dn Slope=0.074417
DSS Import GetInterval= 0
DSS Import GetPeak= 0
DSS Import FillOption= 0

--- LDRYRN.g01 (geometry) ---

Geom Title=Geometry
Program Version=6.20

River Reach=LDRYRN          ,Main
Reach XY= 30
     2217796.308      633180.353     2217637.975       633153.27
     2217567.142      633165.249     2217454.252      633240.913
  2217283.841812633212.7179441032217238.73043941633218.287939171
     2217127.665       633299.59      2217084.85       633309.52
      2217021.71      633282.701     2216937.454      633189.728
2216866.17418178633144.947936232     2216771.829      633219.415
     2216565.058      633268.374     2216471.308      633214.728
     2216360.892      633213.165     2216233.808      633193.374
     2216106.725      633116.811      2216029.09      633095.016
     2215892.684       633095.11     2215775.128       633072.54
     2215636.673      633121.586       2215508.2      633046.065
     2215370.305      633024.963     2215302.472      632995.718
     2215083.287      632986.603     2214929.642      633014.381
     2214759.503      632949.276     2214647.145      632868.855
     2214535.643      632900.291      2214389.47      632846.935

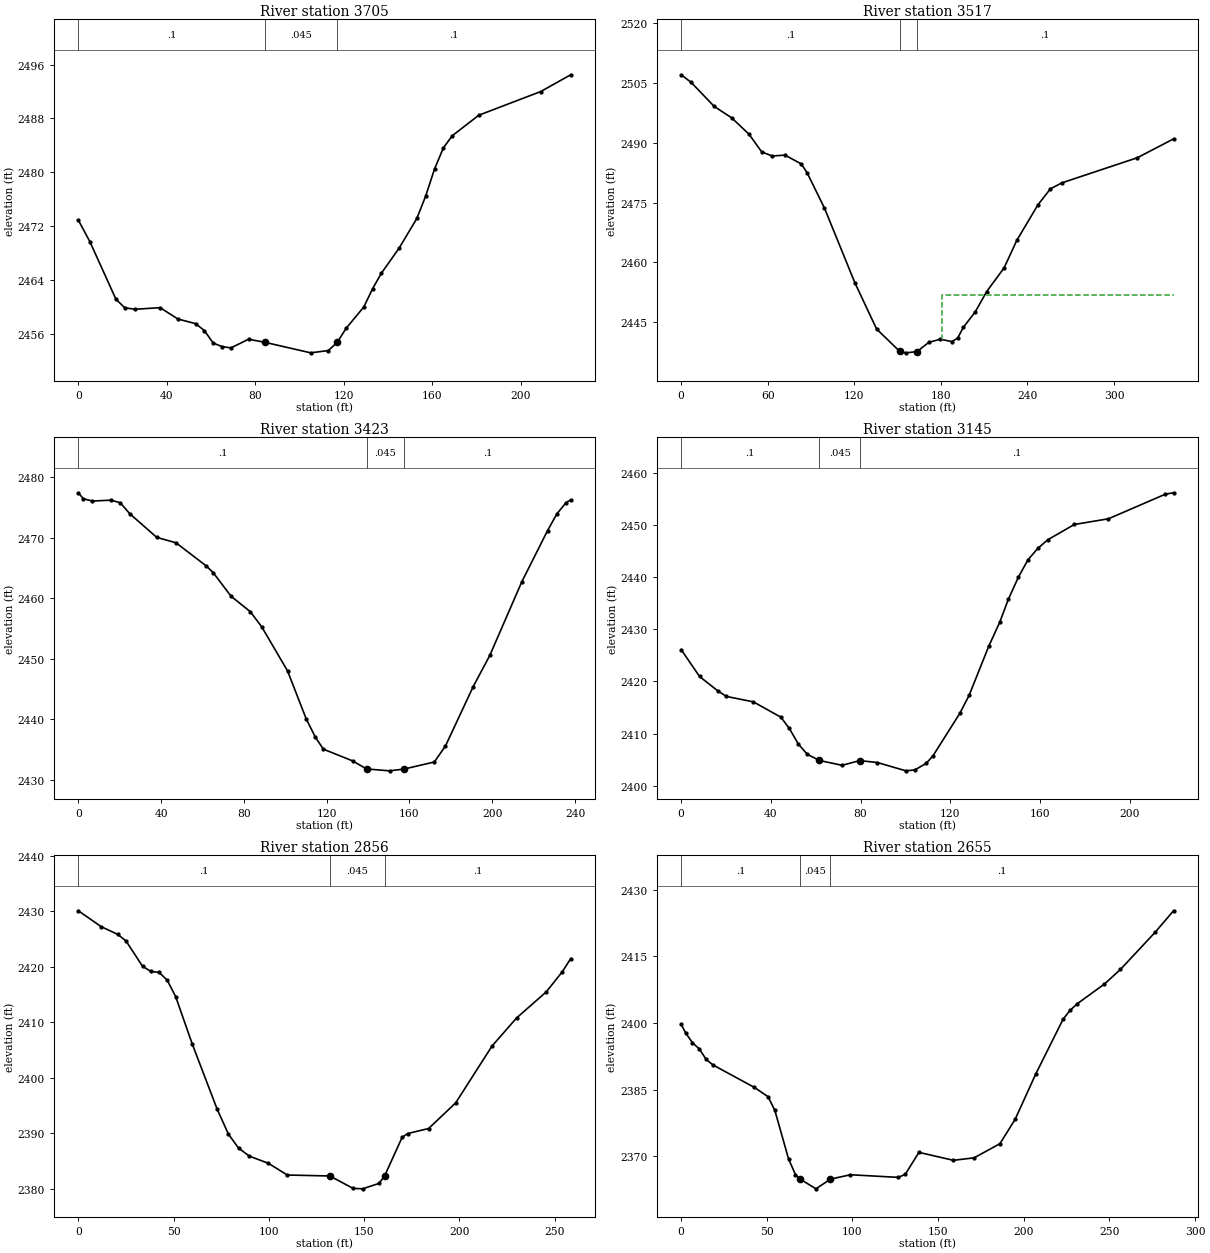
Type RM Length L Ch R = 1 ,3705    ,188.8,187.1,191.4
XS GIS Cut Line= 2
2217788.71868544633092.2399812622217778.48570669633314.669804566
#Sta/Elev= 30
       0 2472.92     5.2 2469.75      17  2461.2      21 2459.93    25.6 2459.71
      37 2459.95      45 2458.27      53 2457.58      57 2456.56      61  2454.7
      65 2454.18      69 2453.98      77 2455.27    84.4 2454.81   105.1 2453.25
   113.1 2453.59   117.1 2454.81   121.1 2456.88   129.1 2460.04   133.1 2462.76
   137.1 2465.07   145.1 2468.78   153.1 2473.17   157.1 2476.49   161.1  2480.5
   165.1 2483.63   169.1 2485.43   181.1 2488.48   209.2    2492   222.7 2494.48
#Mann= 3 ,-1,0
       0      .1       0    84.4    .045       0   117.1      .1       0
Bank Sta=84.4,117.1
XS Rating Curve= 0 ,0
Exp/Cntr=0.3,0.1

Type RM Length L Ch R = 1 ,3517    ,97.1,94.1,93
XS GIS Cut Line= 2
2217586.43032585 632998.324295532217617.15913041633338.097077413
#Sta/Elev= 30
       0 2506.99     6.9 2505.09    22.9 2499.07      35 2496.21      47 2492.12
    55.8 2487.69    63.1 2486.65    71.9 2486.88    83.2 2484.68    87.2 2482.52
    99.3 2473.62   120.4  2454.9   135.4 2443.37   151.5 2437.72   155.8 2437.38
   163.5  2437.7   171.6 2440.01   179.6 2440.79   187.6 2440.19   191.6 2441.07
   195.6  2443.8   203.7 2447.57   211.7 2452.71   223.8 2458.65   232.6 2465.54
   247.3 2474.47   255.9 2478.44   263.9 2479.94   316.1 2486.22   341.2 2490.93
#Mann= 3 ,-1,0
       0      .1       0   151.5    .045       0   163.5      .1       0
#XS Ineff= 2 , 0
                          181.06         2451.95
Permanent Ineff=
       F       F
Bank Sta=151.5,163.5
XS Rating Curve= 0 ,0
Exp/Cntr(USF)=0,0
Exp/Cntr=0.3,0.1

Type RM Length L Ch R = 1 ,3423    ,274.7,278.4,282.5
XS GIS Cut Line= 2
2217451.01008818633067.0814164482217558.84353891633279.119307558
#Sta/Elev= 30
       0 2477.47     2.4 2476.49     6.8  2476.1    15.8 2476.25    20.3 2475.81
    24.8 2474.02    37.9 2470.09    47.2  2469.2    61.9 2465.35    65.2 2464.25
    73.8 2460.36    83.1 2457.81    88.7 2455.26   101.1 2448.01   110.1 2440.09
   114.5 2437.08   118.4 2435.08   132.5 2433.15   139.3 2431.81   150.4  2431.5
   157.4  2431.8     172 2432.96   177.4 2435.62   190.8 2445.43   198.8 2450.57
   214.3 2462.77   226.7  2471.2   231.2 2473.97   235.7 2475.86   237.9 2476.29
#Mann= 3 ,-1,0
       0      .1       0   139.3    .045       0   157.4      .1       0
Bank Sta=139.3,157.4
XS Rating Curve= 0 ,0
Exp/Cntr(USF)=0,0
Exp/Cntr=0.3,0.1

Type RM Length L Ch R = 1 ,3145    ,273.3,289.2,294.3
XS GIS Cut Line= 3
2217255.75022651633148.9839593142217257.39512991633275.183856226
2217295.16230062633360.470265724
#Sta/Elev= 30
       0  2426.1     8.2 2420.95    16.2 2418.24    20.2 2417.13    32.2 2416.09
    44.4 2413.17    48.2 2411.02    52.2 2408.04    56.2 2406.06   61.58 2404.87
    71.7 2403.94    79.6 2404.84    87.5 2404.47   100.2 2402.88   104.2 2403.06
   109.2  2404.3   112.2 2405.71   124.2 2413.87   128.4 2417.36   137.1 2426.72
     142 2431.32   145.9 2435.78   150.3 2439.94   154.6  2443.3     159 2445.49
   163.4 2447.13   175.3 2450.07   190.5 2451.16   215.9 2455.88   219.5 2456.14
#Mann= 3 ,-1,0
       0      .1       0   61.58    .045       0    79.6      .1       0
Bank Sta=61.58,79.6
XS Rating Curve= 0 ,0
Exp/Cntr=0.3,0.1

Type RM Length L Ch R = 1 ,2856    ,206.5,200.6,195.4
XS GIS Cut Line= 4
2217123.26362011633181.6443638542217050.64579986633212.195576564
 2216982.0448431633306.5218921082216979.12999119633369.488462958
#Sta/Elev= 30
       0 2430.05      12 2427.19    20.7 2425.79      25 2424.63    33.7 2420.05
    38.1 2419.12    42.4 2418.96    46.7 2417.52    51.1 2414.58    59.8 2406.05
    72.8 2394.37    78.8  2389.8    84.1  2387.3    89.8 2385.84    99.8 2384.55
   109.7 2382.44  132.072382.266   144.2 2380.04   149.2 2379.95   157.8 2380.92
  160.75 2382.24     170 2389.23   172.9 2389.91   183.9 2390.82   198.1 2395.43
   217.2 2405.68   230.1 2410.74   245.7 2415.45   254.1 2419.07   258.5 2421.43
#Mann= 3 ,-1,0
       0      .1       0  132.07    .045       0  160.75      .1       0
Bank Sta=132.07,160.75
XS Rating Curve= 0 ,0
Exp/Cntr(USF)=0,0
Exp/Cntr=0.3,0.1

Type RM Length L Ch R = 1 ,2655    ,219.9,220.2,217.7
XS GIS Cut Line= 2
2216853.39213364633066.605063421 2216871.3935718633353.428426323
#Sta/Elev= 30
       0 2399.69     2.6 2397.75     6.6 2395.54    10.6 2394.14    14.6 2391.78
    18.6 2390.53    42.7 2385.49    50.7  2383.4    54.7 2380.29    62.7 2369.36
    66.7 2365.87   69.38 2364.86    78.7 2362.65   87.112364.833    98.8 2365.82
   126.8 2365.23   130.8 2365.92   138.8 2370.86   158.9 2369.07     171 2369.63
   186.1 2372.82     195 2378.34     207 2388.52     223 2400.87     227 2402.82
   231.3 2404.34   247.1 2408.76   256.4 2412.03   276.6 2420.37   287.4 2425.24
#Mann= 3 ,-1,0
       0      .1       0   69.38    .045       0   87.11      .1       0
Bank Sta=69.38,87.11
XS Rating Curve= 0 ,0
Exp/Cntr=0.3,0.1

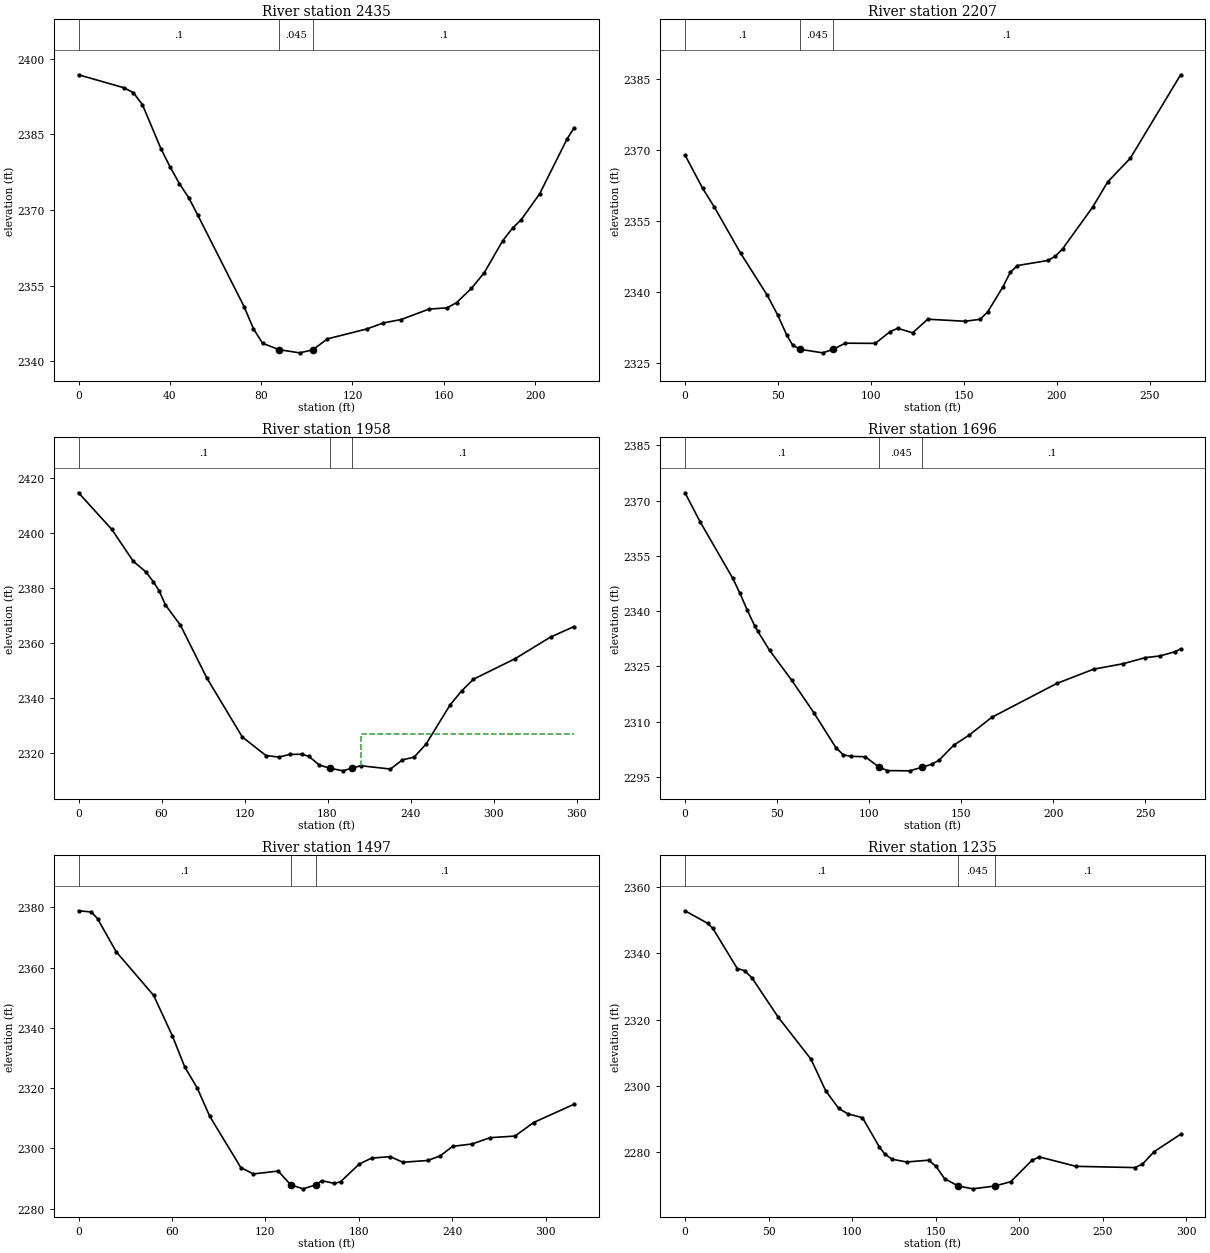
Type RM Length L Ch R = 1 ,2435    ,224.1,228.1,228.4
XS GIS Cut Line= 2
2216655.95610195633145.4562645922216688.47335546633360.070137731
#Sta/Elev= 30
       0 2396.79    19.9 2394.22      24 2393.25      28 2390.87    36.1 2382.15
    40.2 2378.46    44.2 2375.22    48.3 2372.41    52.3 2368.93    72.5 2350.88
    76.6  2346.5    80.6  2343.6    87.8 2342.33    96.8  2341.7  102.522342.273
     109 2344.46   126.4 2346.45   133.5 2347.62   141.3  2348.3   153.5 2350.36
   161.5 2350.62   165.6 2351.65   172.1 2354.48   177.7 2357.56   185.8 2363.91
   190.1 2366.41   193.9 2368.07     202 2373.22   214.1 2384.16   217.1 2386.29
#Mann= 3 ,-1,0
       0      .1       0    87.8    .045       0  102.52      .1       0
Bank Sta=87.8,102.52
XS Rating Curve= 0 ,0
Exp/Cntr(USF)=0,0
Exp/Cntr=0.3,0.1

Type RM Length L Ch R = 1 ,2207    ,247.7,248.4,251
XS GIS Cut Line= 2
2216472.49926864633147.7592295562216436.42905212633412.058711126
#Sta/Elev= 30
       0 2368.95     9.5  2361.9    15.8 2357.93      30 2348.13    44.2 2339.33
    49.9 2335.09    54.8 2330.81      58  2328.7      62 2327.84    74.1  2327.1
    79.7 2327.83    86.2 2329.14   102.4  2329.1   110.4 2331.59   114.5 2332.29
   122.5 2331.33   130.6 2334.21   150.8 2333.78   158.9  2334.2   162.9 2335.78
     171    2341     175 2344.11   178.9 2345.56   195.2 2346.63   199.2  2347.5
   203.3 2349.15   219.4 2357.94   227.5 2363.27   239.6 2368.25   266.7 2385.91
#Mann= 3 ,-1,0
       0      .1       0      62    .045       0    79.7      .1       0
Bank Sta=62,79.7
XS Rating Curve= 0 ,0
Exp/Cntr=0.3,0.1

Type RM Length L Ch R = 1 ,1958    ,268,262.3,259.4
XS GIS Cut Line= 2
2216284.86753165633014.6671972272216156.37493819633349.155853225
#Sta/Elev= 30
       0 2414.62    24.1 2401.26    39.6 2389.66    48.9  2385.7    54.1 2382.18
    58.4 2378.85    62.7 2373.85    73.7 2366.35    92.7 2347.21   118.4 2325.64
   135.5  2318.9   144.9 2318.33   152.7  2319.3   161.2 2319.37   166.6 2318.58
   174.1 2315.41  181.732314.283   191.2 2313.32   197.5  2314.3   204.1 2315.18
   225.5 2313.97   234.1 2317.31   242.6  2318.3   251.2 2323.04   268.7  2337.4
   276.9 2342.41   285.5  2346.7   315.5 2354.15   341.2 2362.05   358.3  2365.9
#Mann= 3 ,-1,0
       0      .1       0  181.73    .045       0   197.5      .1       0
#XS Ineff= 2 , 0
                           203.9         2326.63
Permanent Ineff=
       F       F
Bank Sta=181.73,197.5
XS Rating Curve= 0 ,0
Exp/Cntr(USF)=0,0
Exp/Cntr=0.3,0.1

Type RM Length L Ch R = 1 ,1696    ,198.4,198.8,198.5
XS GIS Cut Line= 2
 2215982.6882071632971.310727756 2215977.6402947633240.337209326
#Sta/Elev= 30
       0 2372.12     8.2 2364.26    25.9 2348.93    29.9 2344.77    33.9 2340.15
    37.9 2335.93    39.6 2334.45    45.9 2329.35    57.9 2321.24    69.9 2312.43
    81.9 2302.92    85.9 2300.98    89.9 2300.55    97.9 2300.42   105.3 2297.61
   109.9 2296.67   121.9  2296.6  128.842297.588     134  2298.4   137.9 2299.48
   145.9 2303.56   154.3  2306.3   166.5 2311.12   201.9 2320.34   221.9 2324.22
   237.9 2325.69   249.9 2327.35   257.9  2327.8   265.9 2328.93   269.1  2329.7
#Mann= 3 ,-1,0
       0      .1       0   105.3    .045       0  128.84      .1       0
Bank Sta=105.3,128.84
XS Rating Curve= 0 ,0
Exp/Cntr=0.3,0.1

Type RM Length L Ch R = 1 ,1497    ,259.2,262.4,268.8
XS GIS Cut Line= 2
2215783.13454766632929.0054682522215785.17411263633247.177604445
#Sta/Elev= 30
       0 2378.86     8.2 2378.47    12.2 2376.26    24.2 2365.25    48.2  2350.8
    60.2 2337.41    68.2 2327.01    76.2 2320.04    84.2 2310.67   104.2 2293.62
   112.2 2291.49   128.2 2292.45   136.2 2287.89   144.2 2286.55  152.522287.892
   156.2 2289.28   164.2 2288.35   168.2 2288.88   180.2 2294.77   188.2 2296.77
   200.2 2297.22   208.2 2295.38   224.2 2295.96   232.2  2297.5   240.2 2300.66
   252.8 2301.46   264.2 2303.53   280.2 2304.07   292.2 2308.57   318.2 2314.66
#Mann= 3 ,-1,0
       0      .1       0   136.2    .045       0  152.52      .1       0
Bank Sta=136.2,152.52
XS Rating Curve= 0 ,0
Exp/Cntr(USF)=0,0
Exp/Cntr=0.3,0.1

Type RM Length L Ch R = 1 ,1235    ,280.2,276.9,272
XS GIS Cut Line= 2
2215617.92978463632916.7680783992215493.51632112633185.990655177
#Sta/Elev= 30
       0 2352.76    13.7 2348.94    16.7 2347.43    31.3 2335.36    35.7 2334.73
    40.1 2332.54    55.9 2320.63    75.4 2308.06    84.2 2298.54      92 2293.23
    97.4 2291.61   106.2 2290.45   116.2 2281.73   119.4 2279.59   123.8 2277.95
   132.6  2277.1   145.9 2277.64   150.3 2275.74   155.3 2272.08   163.5 2269.86
   172.3 2269.01   185.4 2269.86   194.9 2271.15   207.6 2277.58     212 2278.63
     234 2275.79   269.2 2275.41   273.7 2276.43   280.7 2280.19   296.6 2285.45
#Mann= 3 ,-1,0
       0      .1       0   163.5    .045       0   185.4      .1       0
Bank Sta=163.5,185.4
XS Rating Curve= 0 ,0
Exp/Cntr(USF)=0,0
Exp/Cntr=0.3,0.1

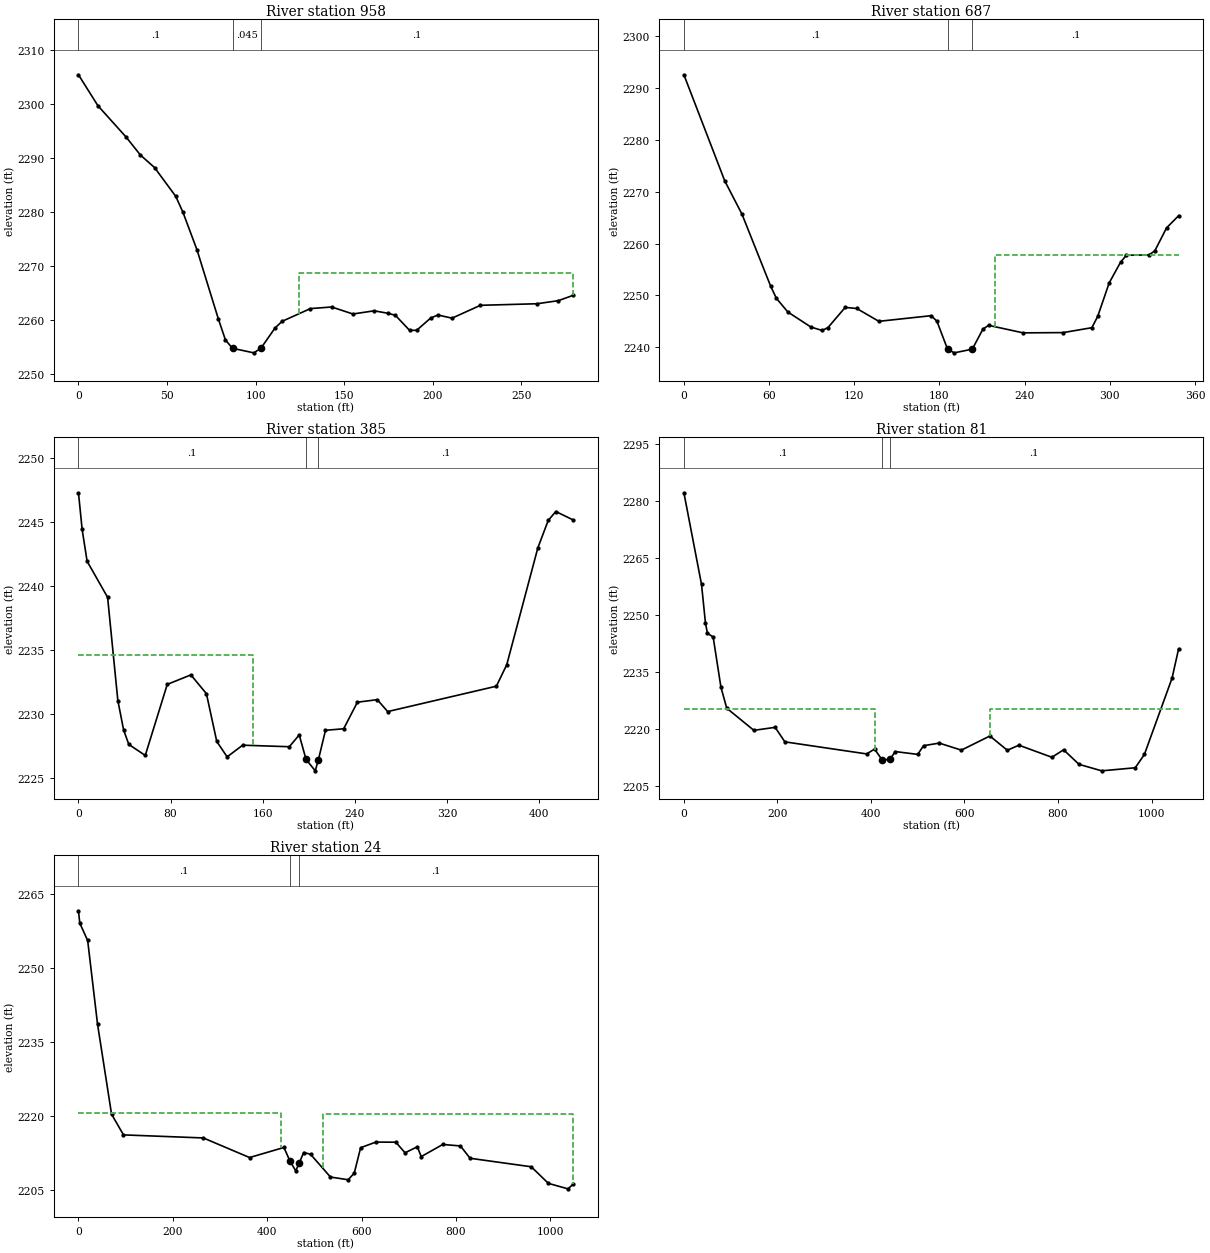
Type RM Length L Ch R = 1 ,958     ,272.5,271,270.3
XS GIS Cut Line= 2
2215284.81700046632898.2162426252215288.43002863633177.623754231
#Sta/Elev= 30
       0 2305.47      11 2299.73      27 2293.89      35 2290.59      43 2288.26
      55 2282.91      59 2279.99      67 2272.97      79 2260.22      83 2256.32
      87 2254.77      99 2253.93     103 2254.76     111 2258.53     115 2259.77
     131 2262.13     143 2262.43     155 2261.13     167 2261.72     175 2261.25
     179 2260.88     187  2258.1     191 2258.11     199  2260.4     203 2260.94
     211 2260.36     227 2262.74     259 2263.03     271  2263.6   279.4 2264.59
#Mann= 3 ,-1,0
       0      .1       0      87    .045       0     103      .1       0
#XS Ineff= 2 , 0
                          124.77         2268.73
Permanent Ineff=
       F       F
Bank Sta=87,103
XS Rating Curve= 0 ,0
Exp/Cntr(USF)=0,0
Exp/Cntr=0.3,0.1

Type RM Length L Ch R = 1 ,687     ,295.2,302.3,304.7
XS GIS Cut Line= 2
2214989.41030496632804.7082867932215038.47611958633149.655831986
#Sta/Elev= 30
       0  2292.6    28.8 2272.08    40.9 2265.67    61.1 2251.76    65.1 2249.43
    73.2 2246.77    89.4 2243.87    97.4  2243.2   101.5 2243.77   113.6 2247.66
   121.7 2247.45   137.3 2244.97   174.2 2246.06   178.2 2244.98   185.7 2239.57
   190.4 2238.88   203.12239.592   210.6 2243.47   214.6 2244.19   238.9 2242.74
   267.1 2242.79   287.3 2243.74   291.4 2245.91   299.5 2252.39   307.5 2256.38
   311.6 2257.73   327.7  2257.8   331.7 2258.62   339.9 2263.02   348.4 2265.37
#Mann= 3 ,-1,0
       0      .1       0   185.7    .045       0   203.1      .1       0
#XS Ineff= 2 , 0
                           219.1         2257.85
Permanent Ineff=
       F       F
Bank Sta=185.7,203.1
XS Rating Curve= 0 ,0
Exp/Cntr(USF)=0,0
Exp/Cntr=0.3,0.1

Type RM Length L Ch R = 1 ,385     ,304.3,303.8,304.4
XS GIS Cut Line= 2
2214827.40390615 632750.334443142214631.14064768633132.453060012
#Sta/Elev= 30
       0 2247.25     3.2 2244.39     7.5 2241.91    25.3  2239.1    34.2 2231.05
    39.2 2228.76    43.7 2227.63      58 2226.77    77.1 2232.31    97.6 2233.05
   111.1 2231.59   120.1 2227.86   129.1 2226.66   142.6 2227.57   183.1 2227.45
   191.7 2228.37   197.6 2226.47   205.6 2225.57   208.4 2226.45   214.5 2228.73
   230.3 2228.85   242.2 2230.92   259.5 2231.12   268.5 2230.19   362.9 2232.17
   371.9 2233.84   398.9 2242.95   407.9 2245.09   414.5 2245.79   429.6 2245.13
#Mann= 3 ,-1,0
       0      .1       0   197.6    .045       0   208.4      .1       0
#XS Ineff= 2 , 0
          151.18 2234.63
Permanent Ineff=
       F       F
Bank Sta=197.6,208.4
XS Rating Curve= 0 ,0
Exp/Cntr(USF)=0,0
Exp/Cntr=0.3,0.1

Type RM Length L Ch R = 1 ,81      ,56.5,56.3,56.3
XS GIS Cut Line= 5
2214868.60827846632731.2899585552214617.15113904632799.003525138
 2214475.5606714632841.8080210662214423.65383453633006.045060329
2214548.26308806633466.780753543
#Sta/Elev= 30
       0 2282.26    37.7 2258.12      46  2248.1    50.2 2245.31    62.6 2244.28
    79.2 2231.08    91.6 2225.56   149.6 2219.73   195.1 2220.52   215.9  2216.7
     391 2213.52   407.7 2214.81  424.072211.903440.66912212.126     452 2214.14
     500  2213.4   512.5 2215.69   546.1 2216.37   593.3 2214.52   654.3 2218.24
   691.6 2214.49   716.4 2215.82   786.9 2212.64   811.9 2214.61   844.9 2210.78
   893.4 2209.07   965.2 2209.88   984.7 2213.38  1043.8 2233.44  1057.9 2241.19
#Mann= 3 ,-1,0
       0      .1       0  424.07    .045       0440.6691      .1       0
#XS Ineff= 2 , 0
          408.74 2225.41  653.55         2225.41
Permanent Ineff=
       F       F
Bank Sta=424.07,440.6691
XS Rating Curve= 0 ,0
Exp/Cntr(USF)=0,0
Exp/Cntr=0.3,0.1

Type RM Length L Ch R = 1 ,24      ,,,
XS GIS Cut Line= 4
2214826.63300474632684.507220729 2214422.7695988632820.262147295
2214381.67856081632959.2623225032214506.28781434633419.998015717
#Sta/Elev= 30
       0 2261.57     2.8 2259.06    19.5 2255.55    40.4 2238.61    70.1 2220.37
    95.4 2216.17   264.6 2215.55   362.5 2211.58   435.4 2213.62   448.2 2210.85
   460.4 2208.89   467.5 2210.38   477.1  2212.6   491.7 2212.25     534 2207.63
   571.4 2207.08   584.4 2208.42   597.9 2213.57   630.1 2214.71   672.5 2214.69
     692 2212.54     718 2213.76   726.3 2211.77   771.9 2214.23   809.4 2213.93
   829.9 2211.43   959.5 2209.71   995.7 2206.35  1037.1 2205.24  1048.3 2206.17
#Mann= 3 ,-1,0
       0      .1       0   448.2    .045       0   467.5      .1       0
#XS Ineff= 2 , 0
          428.42 2220.69  518.03          2220.5
Permanent Ineff=
       F       F
Bank Sta=448.2,467.5
XS Rating Curve= 0 ,0
Exp/Cntr(USF)=0,0
Exp/Cntr=0.3,0.1
LCMann Table=0

Chan Stop Cuts=-1
Use User Specified Reach Order=0
Composite Channel Slope=5